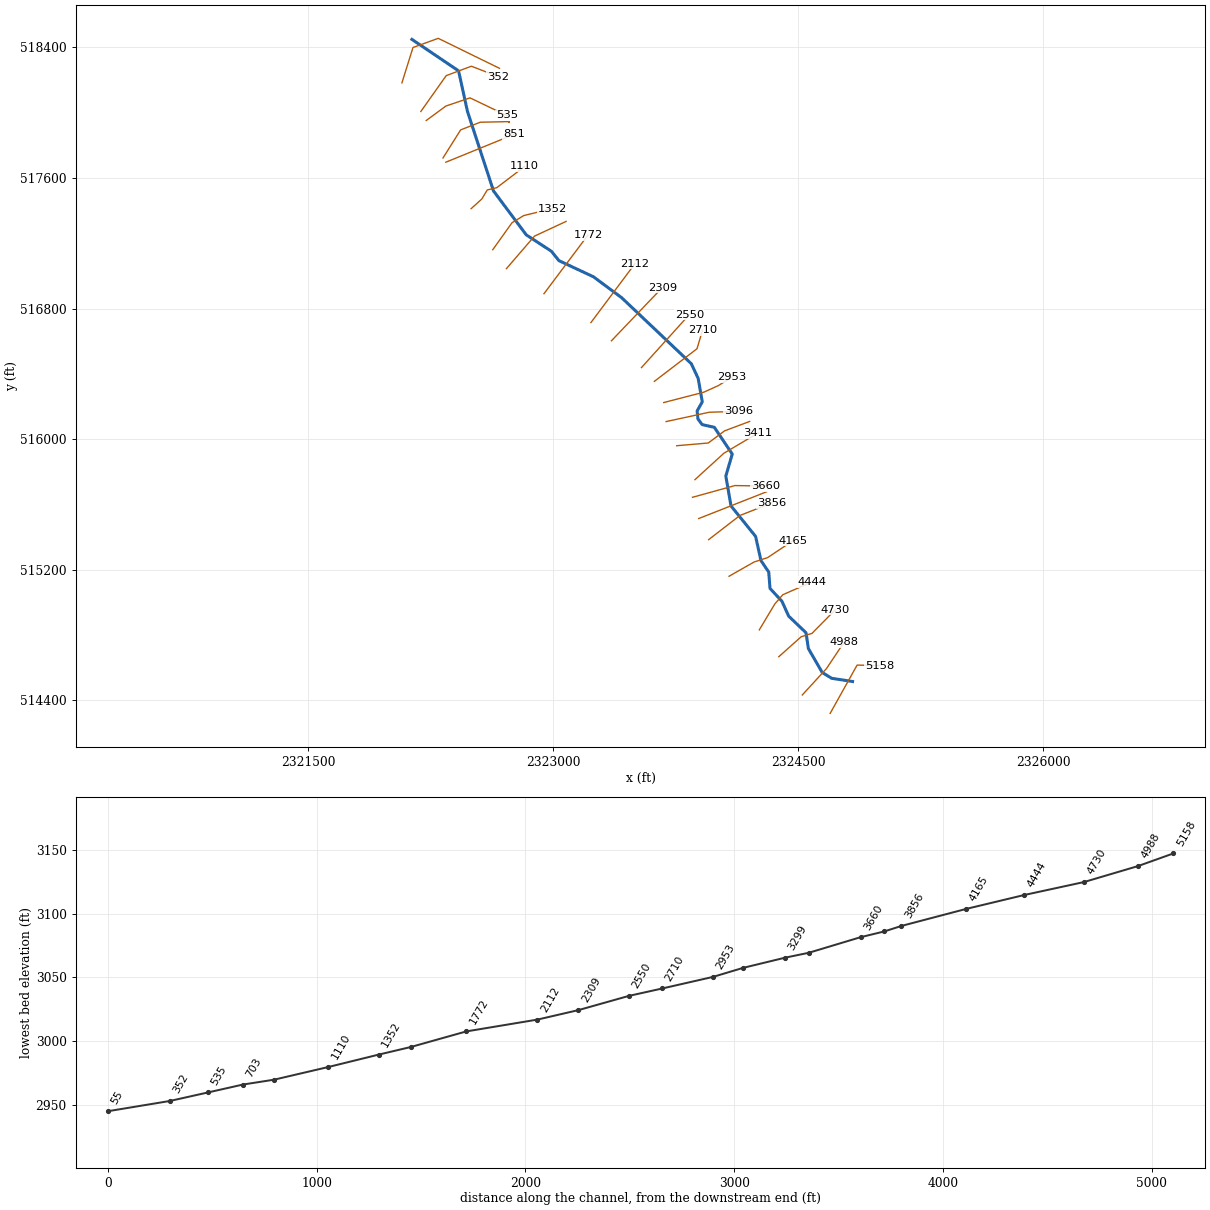
--- STTNRN.prj (project) ---

Proj Title=STTNRN
Current Plan=p01
Default Exp/Contr=0,0
English Units
Geom File=g01
Flow File=f01
Plan File=p01
Background Map Layer=Inundation Boundary (01pct Value_0)
BEGIN DESCRIPTION:
----------MODEL BY WOOD PLC 2021----------
Stream Name: Sutton Run
Flood Zone: Enhanced Approximate
Pocahontas County, WV
HEC-RAS Version: RAS 6.1
Vertical Datum: NAVD88
Projection: NAD 1983 StatePlane West Virginia S FIPS 4702 (US Feet)
Terrain: 1-meter LIDAR (FEMA Region III 3DEP collected 2016-2018)
Land Use: 2019 NLCD
Hydrologic Method:
WV SIR2010-5033 regression equations
Model Notes:
Normal depth tie in to North Fork
END DESCRIPTION:
DSS Export Rating Curves= 0
DSS Export Rating Curve Sorted= 0
DSS Export Volume Flow Curves= 0
DXF OffsetX= 0
DXF OffsetY= 0
DXF ScaleX= 0
DXF ScaleY= 0

--- STTNRN.p01 (plan) ---

Plan Title=Floodplain
Program Version=6.10
Short Identifier=Floodplain
Geom File=g01
Flow File=f01
Subcritical Flow
K Sum by GR= 0
Std Step Tol= 0.01
Critical Tol= 0.01
Num of Std Step Trials= 20
Max Error Tol= 0.3
Flow Tol Ratio= 0.001
Split Flow NTrial= 30
Split Flow Tol= 0.02
Split Flow Ratio= 0.02
Log Output Level= 0
Friction Slope Method= 1
Unsteady Friction Slope Method= 2
Unsteady Bridges Friction Slope Method= 1
Parabolic Critical Depth
Global Vel Dist= 0 , 0 , 0
Global Log Level= 0
CheckData=True
Encroach Param=-1 ,0,0, 0
Mapping Interval=1HOUR
Computation Time Step Use Courant=        0
Computation Time Step Use Time Series=    0
Computation Time Step Count To Double=0
Computation Time Step Max Doubling=0
Computation Time Step Max Halving=0
Computation Time Step Residence Courant=0
Run HTab= 0
Run UNet= 0
Run Sediment= 0
Run PostProcess= 0
Run WQNet= 0
Run RASMapper=-1
UNET Theta= 0
UNET Theta Warmup= 0
UNET ZTol= 0
UNET ZSATol= 0
UNET MxIter= 0
UNET Max Iter WO Improvement= 0
UNET MaxInSteps= 0
UNET DtIC= 0
UNET DtMin= 0
UNET MaxCRTS= 0
UNET WFStab= 0
UNET SFStab= 0
UNET WFX= 1
UNET SFX= 1
UNET Gravity=32.174
UNET 1D Methodology=Finite Difference
UNET DSS MLevel= 1
UNET Pardiso=0
UNET DZMax Abort= 0
UNET Use Existing IB Tables= 0
UNET Froude Reduction=False
UNET Froude Limit= 0
UNET Froude Power= 0
UNET D1 Cores= 0
UNET WindReference=Eulerian
UNET WindDragFormulation=Hsu (1988)
UNET D2 Coriolis=0
UNET D2 Cores= 0
UNET D2 Theta= 1
UNET D2 Theta Warmup= 1
UNET D2 Z Tol= 0.01
UNET D2 Volume Tol= 0.01
UNET D2 Max Iterations= 20
UNET D2 Equation= 0
UNET D2 RampUpFraction=0.1
UNET D2 TimeSlices= 1
UNET D2 Turbulence Formulation=Non-Conservative (original)
UNET D2 Eddy Viscosity=0.3
UNET D2 Transverse Eddy Viscosity=0.1
UNET D2 Smagorinsky Mixing=0
UNET D2 BCVolumeCheck=0
UNET D2 Cores=0
UNET D2 SolverType=PARDISO (Direct)
UNET D2 Minimum Iterations= 2147483647
UNET D2 Maximum Iterations= 2147483647
UNET D2 Restart Number= 10
UNET D2 Relaxation Coeff=1.3
UNET D2 SOR Precondition Iterations= 10
UNET D2 ILUT Maximum Fill= 8
UNET D2 ILUT Tolerance=1E-08
UNET D1D2 MaxIter= 0
UNET D1D2 ZTol=0.01
UNET D1D2 QTol=0.1
UNET D1D2 MinQTol=1
Write IC File= 0
Write IC File at Fixed DateTime=0
Write IC File at Sim End=0
Echo Input=False
Echo Parameters=False
Echo Output=False
Write Detailed= 0
HDF Write Warmup=0
HDF Write Time Slices=0
HDF Flush=0
HDF Compression= 1
HDF Chunk Size= 1
HDF Spatial Parts= 1
HDF Use Max Rows=0
HDF Fixed Rows= 1
Calibration Method= 0
Calibration Iterations= 20
Calibration Max Change=0.05
Calibration Tolerance=0.2
Calibration Maximum=1.5
Calibration Minimum=0.5
Calibration Optimization Method= 1
WQ AD Non Conservative
WQ ULTIMATE=-1
WQ Max Comp Step=1HOUR
WQ Output Interval=15MIN
WQ Output Selected Increments= 0
WQ Output face flow=0
WQ Output face velocity=0
WQ Output face area=0
WQ Output face dispersion=0
WQ Output cell volume=0
WQ Output cell surface area=0
WQ Output cell continuity=0
WQ Output cumulative cell continuity=0
WQ Output face conc=0
WQ Output face dconc_dx=0
WQ Output face courant=0
WQ Output face peclet=0
WQ Output face adv mass=0
WQ Output face disp mass=0
WQ Output cell mass=0
WQ Output cell source sink temp=0
WQ Output nsm pathways=0
WQ Output nsm derived pathways=0
WQ Create Restart=0
WQ Fixed Restart=0
WQ System Summary=0
WQ Write To DSS=0
Sorting and Armoring Iterations= 10
XS Update Threshold= 0.02
Bed Roughness Predictor= 0
Hydraulics Update Threshold= 0.02
Energy Slope Method= 1
Volume Change Method= 1
Sediment Retention Method= 0
Sediment TS Multiplier= 1
Warm Up Method= 0
XS Weighting Method= 0
Number of US Weighted Cross Sections= 1
Number of DS Weighted Cross Sections= 1
Upstream XS Weight=0
Main XS Weight=1
Downstream XS Weight=0
Number of DS XS's Weighted with US Boundary= 1
Upstream Boundary Weight= 1
Weight of XSs Associated with US Boundary= 0
Number of US XS's Weighted with DS Boundary= 1
Downstream Boundary Weight= 0.5
Weight of XSs Associated with DS Boundary= 0.5
Percentile Method= 0
Sediment Output Level= 3
Mass or Volume Output= 0
Output Increment Type= 1
Profile and TS Output Increment= 1
Transport Output Increment 1
XS Output Flag= 0
XS Output Increment= 10
Read HDF5 Sediment Hotstart= 0
Sediment Hotstart Type= 0
Write Gradation File= 0
Read Gradation Hotstart= 0
Write HDF5 File= 1
Write Binary Output= 1
Write DSS Sediment File= 0
DSS Sediment Output Type= 1
SV Curve= 0
Specific Gage Flag= 0
Subcell Erosion Methods= 0
Subcell Deposition Methods= 0
Advection Scheme= 1
Matrix Solver= 0
Implicit Weighting Factor= 1
Maximum Outer Loop Convergence Iterations= 5
Convergence Maximum Absolute= 0.001
Convergence RMSE= 0.0001
Grain Fractions Max Abs Error= 0.001
Max Subgrid Regions= 1
Max Subgrid Length Scale= 3.402823E+38
Initial Layer Thickness= 3.402823E+38
Min Layer Thickness= 3.402823E+38
Max Layer Thickness= 3.402823E+38
Number of Layers= 5

--- STTNRN.f01 (steady flow) ---

Flow Title=Flow
Program Version=6.10
Number of Profiles= 6
Profile Names=01pct,10pct,04pct,02pct,0_2pct,01plus
River Rch & RM=STTNRN,Main,5158
     561     296     394     475     784     830
River Rch & RM=STTNRN,Main,2953
     706     376     498     598     982    1040
Boundary for River Rch & Prof#=STTNRN,Main            , 1
Up Type= 0
Dn Type= 3
Dn Slope=0.02742
Boundary for River Rch & Prof#=STTNRN,Main            , 2
Up Type= 0
Dn Type= 3
Dn Slope=0.02742
Boundary for River Rch & Prof#=STTNRN,Main            , 3
Up Type= 0
Dn Type= 3
Dn Slope=0.02742
Boundary for River Rch & Prof#=STTNRN,Main            , 4
Up Type= 0
Dn Type= 3
Dn Slope=0.02742
Boundary for River Rch & Prof#=STTNRN,Main            , 5
Up Type= 0
Dn Type= 3
Dn Slope=0.02742
Boundary for River Rch & Prof#=STTNRN,Main            , 6
Up Type= 0
Dn Type= 3
Dn Slope=0.02742
DSS Import GetInterval= 0
DSS Import GetPeak= 0
DSS Import FillOption= 0

--- STTNRN.g01 (geometry) ---

Geom Title=Geometry
Program Version=6.10

River Reach=STTNRN          ,Main
Reach XY= 30
     2324831.993      514516.1452324703.78212497514536.015891521
     2324646.061      514571.639     2324561.422      514718.084
     2324546.924      514814.929     2324441.143      514915.974
     2324399.486      515007.611     2324326.396      515086.359
     2324318.798      515186.145     2324271.238      515256.658
     2324238.122      515404.818     2324087.687      515591.422
     2324056.021      515773.922     2324095.215      515909.189
     2323985.451      516072.769     2323911.291      516089.294
     2323885.187      516123.9222323880.26110083516173.221416619
2323911.79798006516228.701255001     2323886.435       516372.53
     2323844.743      516462.008     2323417.915      516866.503
     2323245.491       516994.492323034.15170899517093.351003012
2322987.41088578517151.2776642612322834.00510702517251.151218138
2322633.30659529517520.0898622542322473.92320387518006.866536291
2322419.50892968518255.4961896762322133.63462517518448.315947904

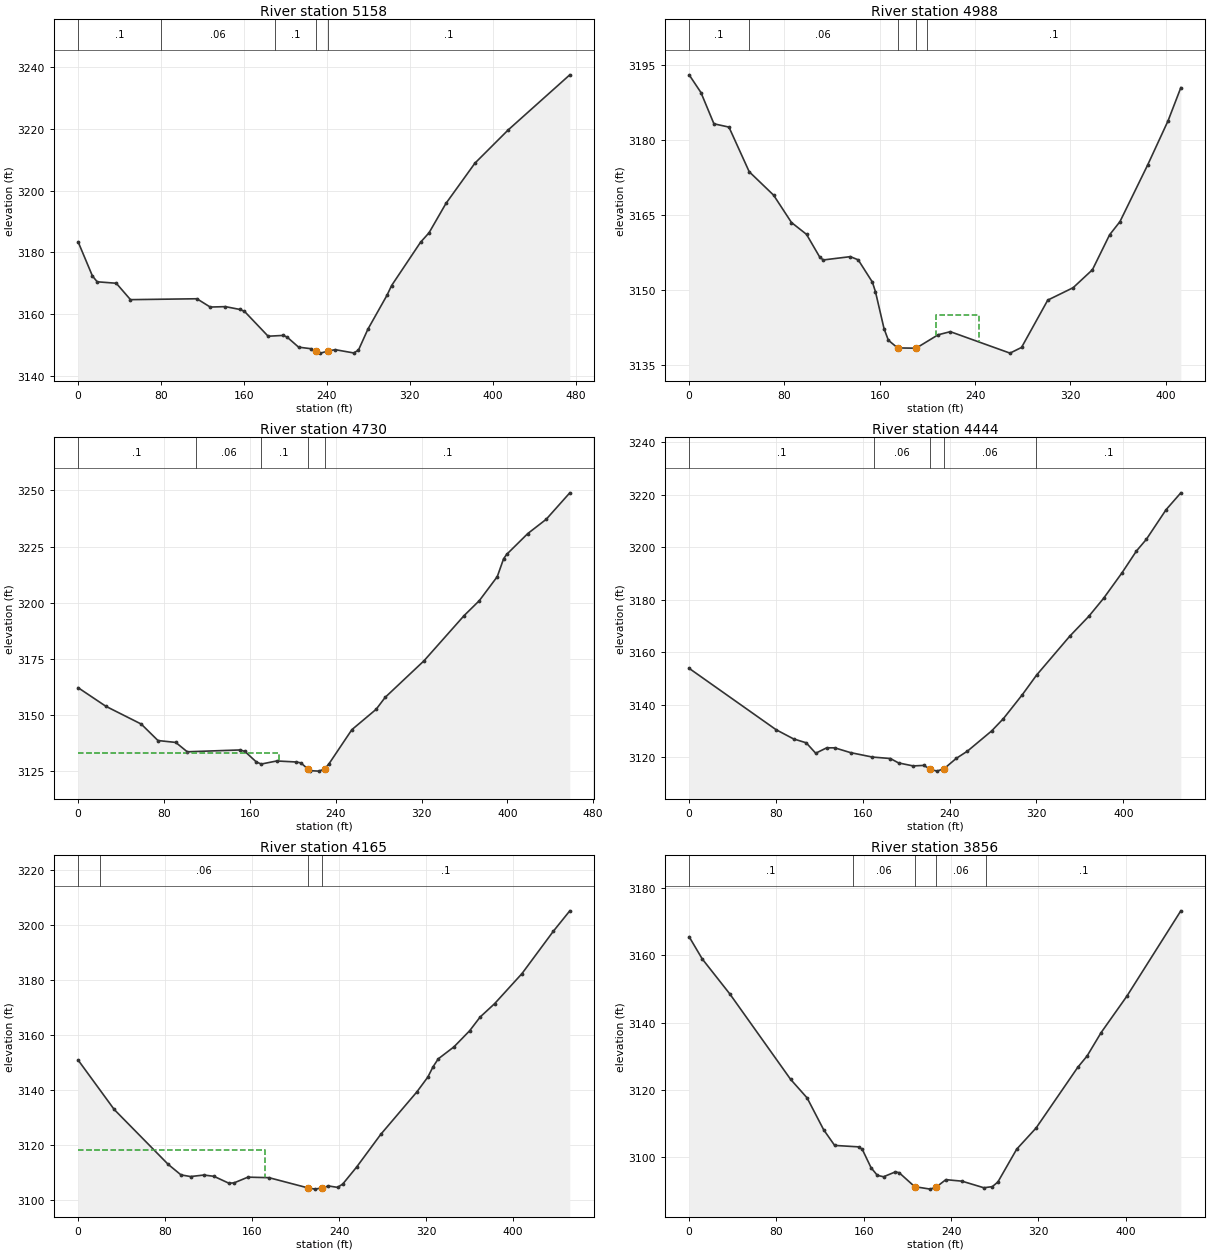
Type RM Length L Ch R = 1 ,5158    ,170.4,170.4,170.4
XS GIS Cut Line= 3
2324694.87977346 514321.088388992324859.86607722514616.688849897
 2324995.6314466514614.205610883
#Sta/Elev= 30
       0 3183.43    13.8 3172.39    18.4 3170.51    36.8 3170.04    50.5 3164.73
   114.6 3165.02   127.4 3162.34   142.1 3162.47   155.9 3161.57   160.4 3160.97
   183.3  3152.9     198 3153.16   201.7 3152.59   212.7 3149.36   224.6 3148.86
   229.1 3148.11   233.7 3147.43   240.7 3148.06     248 3148.55   265.8 3147.49
   270.4 3148.39   279.5 3155.16     298 3166.18   302.4  3169.3   330.3  3183.3
   338.5 3186.36   354.8 3195.85   382.8  3208.9   414.8 3219.62   474.3 3237.47
#Mann= 5 ,-1,0
       0      .1       0      80     .06       0     190      .1       0
   229.1    .045       0   240.7      .1       0
Bank Sta=229.1,240.7
XS Rating Curve= 0 ,0
Exp/Cntr(USF)=0,0
Exp/Cntr=0.3,0.1

Type RM Length L Ch R = 1 ,4988    ,264.9,258.3,251.4
XS GIS Cut Line= 3
 2324524.2957567514433.8741646752324672.38436946514595.493716676
2324779.88016451514756.361549831
#Sta/Elev= 30
       0 3193.08     9.9 3189.54    20.8 3183.29    33.4 3182.63    50.4 3173.71
    70.9 3169.02    85.9 3163.55    98.5 3161.19   109.8 3156.56   112.7 3156.07
   135.3 3156.73   141.9 3156.09   153.8 3151.64   156.4  3149.7   163.6 3142.32
   167.2 3140.02     175 3138.48  190.493138.427   208.9  3141.1   219.2 3141.73
   269.3 3137.44     279 3138.58     301 3148.04   322.3 3150.52   338.5 3154.11
   352.9 3161.09   361.6 3163.73   384.8 3175.03     402  3183.9   412.7 3190.52
#Mann= 5 ,-1,0
       0      .1       0      50     .06       0     175    .045       0
  190.49     .06       0     200      .1       0
#XS Ineff= 1 ,-1
  206.81  243.363145.153
Permanent Ineff=
       F
Bank Sta=175,190.49
XS Rating Curve= 0 ,0
Exp/Cntr(USF)=0,0
Exp/Cntr=0.3,0.1

Type RM Length L Ch R = 1 ,4730    ,279,285.3,292.5
XS GIS Cut Line= 4
2324380.33986929514667.9465656642324517.11137372514790.194949604
2324583.48063068514810.8972866372324727.65409631 514956.98749205
#Sta/Elev= 30
       0  3162.1    25.9  3153.8    58.8 3145.89    74.4 3138.55      91  3137.7
   101.7 3133.53   150.9 3134.35   155.4 3133.69   166.1 3128.99   170.7 3128.07
   185.1 3129.44   203.4 3128.98   207.6 3128.58     214  3125.9     216 3125.12
   224.4 3124.91   229.8 3125.87   233.8 3128.19   255.1 3143.39   277.7 3152.46
   286.2 3157.82   322.3 3174.08   359.7 3194.24   373.9 3200.91   390.6  3211.6
   396.5 3219.56   399.3 3221.49   419.1 3230.83   436.2 3237.16   458.2 3248.96
#Mann= 5 ,-1,0
       0      .1       0     110     .06       0     170      .1       0
     214    .045       0   229.8      .1       0
#XS Ineff= 2 , 0
          186.98 3132.78
Permanent Ineff=
       F       F
Bank Sta=214,229.8
XS Rating Curve= 0 ,0
Exp/Cntr(USF)=0,0
Exp/Cntr=0.3,0.1

Type RM Length L Ch R = 1 ,4444    ,284.9,278.8,272.7
XS GIS Cut Line= 4
2324260.95332288514832.4425459592324356.34048224514991.780588993
2324404.59897609515047.4634665132324581.80912918 515125.45670309
#Sta/Elev= 30
       0 3153.92    80.1 3130.54    96.2 3127.04   107.9 3125.54   116.6 3121.58
   126.7 3123.64   134.1 3123.64   148.7 3121.81   168.7 3120.13   185.4 3119.56
   192.9 3117.89   206.4 3116.74     216 3116.94   222.1 3115.54   228.2 3114.76
   234.8 3115.65   246.1 3119.62   256.4 3122.38   278.6 3130.04   289.5 3134.75
     307  3143.9   320.1 3151.35   350.7 3166.19   368.2 3173.74   381.8 3180.58
   398.8 3190.32   412.1 3198.63   421.2 3203.06   439.4 3214.36     453 3220.79
#Mann= 5 ,-1,0
       0      .1       0     170     .06       0   222.1    .045       0
   234.8     .06       0  319.39      .1       0
Bank Sta=222.1,234.8
XS Rating Curve= 0 ,0
Exp/Cntr(USF)=0,0
Exp/Cntr=0.3,0.1

Type RM Length L Ch R = 1 ,4165    ,304.7,309.7,312.7
XS GIS Cut Line= 4
2324075.56515399515160.7594790692324229.10533205515248.081933394
2324311.91468018515274.8731930842324468.77611005515379.586223391
#Sta/Elev= 30
       0  3150.8    33.2  3132.8    82.9  3112.8    94.6 3108.99   103.4 3108.38
   115.7 3108.93   124.9 3108.47   138.6 3105.97   143.4 3106.07   156.2 3108.16
   175.6 3107.97   211.7 3104.22   218.1  3103.8   224.4 3104.28   230.3 3104.95
   238.7 3104.44   243.5 3105.69   256.2 3111.84   278.4 3123.75   311.7 3139.25
   321.7 3144.61   326.5 3148.36   331.3 3151.25   345.7  3155.6   360.2 3161.49
   369.8 3166.47   383.1 3171.33   408.3 3182.29   437.1 3197.69   452.3 3205.15
#Mann= 4 ,-1,0
       0      .1       0      20     .06       0   211.7    .045       0
   224.4      .1       0
#XS Ineff= 2 , 0
          172.11 3118.08
Permanent Ineff=
       F       F
Bank Sta=211.7,224.4
XS Rating Curve= 0 ,0
Exp/Cntr(USF)=0,0
Exp/Cntr=0.3,0.1

Type RM Length L Ch R = 1 ,3856    ,85.5,81.7,78.6
XS GIS Cut Line= 3
 2323950.6655677515384.8132782432324142.20968257515532.839163703
2324336.11497261515609.364498631
#Sta/Elev= 30
       0 3165.55      12 3158.95    37.3 3148.52    92.9 3123.14   108.1 3117.58
   123.2 3108.13   133.3 3103.45   155.3 3103.02   158.6  3102.3   166.7  3096.8
   172.4 3094.55   178.1 3094.12     189 3095.58   192.4 3095.33   206.6 3091.19
   206.6 3091.18   220.9 3090.44   226.6 3091.09   235.2 3093.26     250 3092.81
     270 3090.85   277.8 3091.18   282.9 3092.58   300.1 3102.33   317.9 3108.64
     356 3126.67   364.6 3130.06   377.5 3137.05   401.1 3147.89   450.5 3173.27
#Mann= 5 ,-1,0
       0      .1       0     150     .06       0   206.6    .045       0
   226.6     .06       0  272.08      .1       0
Bank Sta=206.6,226.6
XS Rating Curve= 0 ,0
Exp/Cntr(USF)=0,0
Exp/Cntr=0.3,0.1

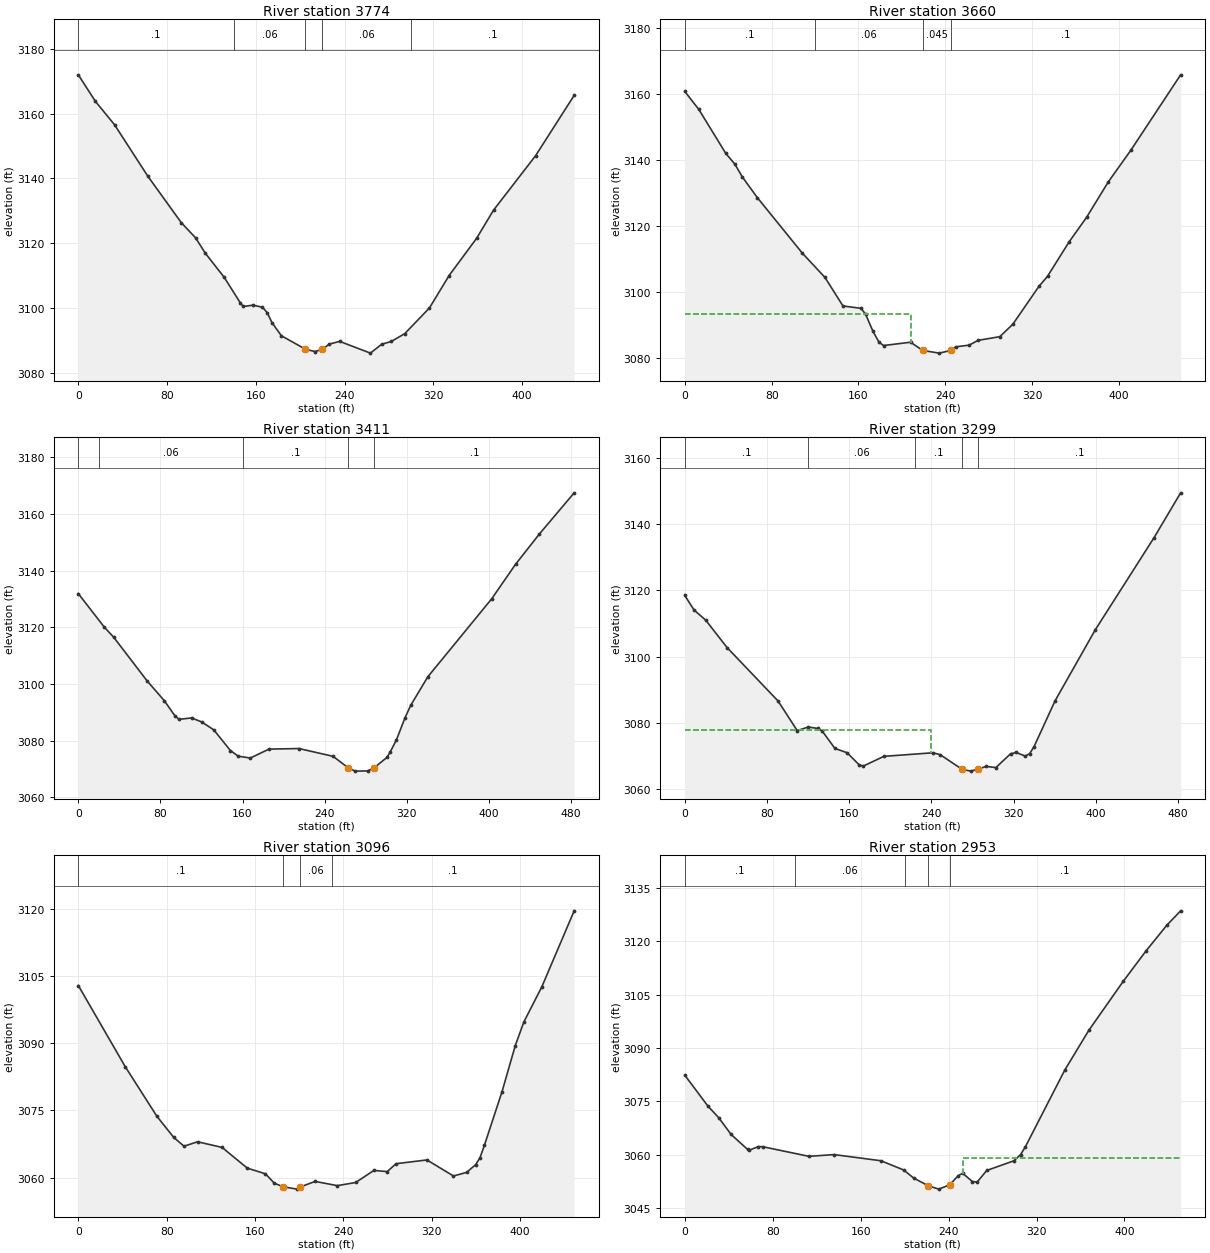
Type RM Length L Ch R = 1 ,3774    ,115.4,114.2,112.7
XS GIS Cut Line= 2
2323889.84505024515514.0941471192324305.54557236 515677.96885566
#Sta/Elev= 30
       0 3171.95    15.4 3163.76    32.6 3156.57    62.7 3140.65    92.8 3126.36
   105.7 3121.67   114.3    3117   131.5 3109.49     146 3101.61   148.7 3100.52
   157.3 3100.92   165.9 3100.29   170.2 3098.62   174.5 3095.53     183 3091.48
   204.7 3087.33   213.2 3086.62     220 3087.31   226.1 3088.91   235.5 3089.75
   263.2 3086.13   273.4 3088.88     282 3089.72   294.1 3092.13   316.4 3100.06
   334.1 3110.06   358.8 3121.49   374.2 3130.24     412 3146.99   446.8 3165.61
#Mann= 5 ,-1,0
       0      .1       0     140     .06       0   204.7    .045       0
     220     .06       0     300      .1       0
Bank Sta=204.7,220
XS Rating Curve= 0 ,0
Exp/Cntr(USF)=0,0
Exp/Cntr=0.3,0.1

Type RM Length L Ch R = 1 ,3660    ,244.7,248.8,251.3
XS GIS Cut Line= 3
2323851.72237583515644.2839794992324111.76027935515716.144571106
2324298.71961514515713.099630783
#Sta/Elev= 30
       0 3160.84    12.9 3155.41    37.8 3142.06    46.1 3138.83    53.1  3134.9
    66.9 3128.65   108.4 3111.82   129.1 3104.53   145.7 3095.87   162.3 3095.15
   166.5 3093.42   173.4 3088.17   178.9  3084.9   183.1 3083.88     208 3084.88
   219.33082.383   234.5 3081.58   245.3 3082.42   249.5 3083.49   261.9 3083.99
   270.2 3085.45   290.2 3086.56   302.2 3090.33   326.2 3101.77   334.2 3104.87
   354.2 3115.35   370.2 3122.73   390.2 3133.47   410.9 3143.02   456.8 3165.88
#Mann= 4 ,-1,0
       0      .1       0     120     .06       0   219.3    .045       0
   245.3      .1       0
#XS Ineff= 2 , 0
          208.73 3093.54
Permanent Ineff=
       F       F
Bank Sta=219.3,245.3
XS Rating Curve= 0 ,0
Exp/Cntr(USF)=0,0
Exp/Cntr=0.3,0.1

Type RM Length L Ch R = 1 ,3411    ,110.7,112.2,113.5
XS GIS Cut Line= 3
2323866.75603183515752.0950647842324044.02306465515914.070965261
2324253.32132011 516037.72628956
#Sta/Elev= 30
       0 3131.94    25.3 3120.12    34.4 3116.59    66.9  3101.2    83.9 3094.11
      94 3088.88      98 3087.58   110.3 3088.06   120.2 3086.67     132 3083.86
   148.2 3076.58   155.8 3074.58   167.6 3073.92   185.8 3077.07   215.1 3077.27
   248.3 3074.52   262.9 3070.49   269.8  3069.3   282.1 3069.37   288.5 3070.55
   300.7 3074.13   303.8 3075.96     310 3080.32   318.4 3088.16   323.9 3092.51
   340.6  3102.6   402.9 3130.15   426.1 3142.31   449.4 3153.03   483.2 3167.52
#Mann= 5 ,-1,0
       0      .1       0      20     .06       0     160      .1       0
   262.9    .045       0   288.5      .1       0
Bank Sta=262.9,288.5
XS Rating Curve= 0 ,0
Exp/Cntr(USF)=0,0
Exp/Cntr=0.3,0.1

Type RM Length L Ch R = 1 ,3299    ,208,202.6,197.3
XS GIS Cut Line= 4
 2323755.2066975515960.0594266632323948.22271915 515976.66101364
2324048.70151716 516051.356318232324201.86133447 516108.66775986
#Sta/Elev= 30
       0 3118.44       9 3114.06    20.4 3110.98    41.1 3102.74    90.7 3086.65
   109.4 3077.72   120.2 3078.78   129.4 3078.36   133.5 3077.66   146.1 3072.34
     158 3071.03   169.6 3067.41   173.6 3067.01   193.7 3069.95   241.5 3071.03
   248.4 3070.48   269.93066.039   278.4  3065.5285.46953066.125   293.4 3066.92
   302.7 3066.57     317 3070.72   322.6 3071.12   331.2 3070.03   335.5 3070.75
   339.7 3072.77   360.3 3086.68   399.5 3108.11   456.7 3135.88   482.5 3149.36
#Mann= 5 ,-1,0
       0      .1       0     120     .06       0  223.73      .1       0
   269.9    .045       0285.4695      .1       0
#XS Ineff= 2 , 0
             240 3077.79
Permanent Ineff=
       F       F
Bank Sta=269.9,285.4695
XS Rating Curve= 0 ,0
Exp/Cntr(USF)=0,0
Exp/Cntr=0.3,0.1

Type RM Length L Ch R = 1 ,3096    ,141.4,143.6,143.7
XS GIS Cut Line= 3
2323690.63955591516107.9520358672323954.49287104516165.082668202
2324133.40195651516170.344700128
#Sta/Elev= 30
       0 3102.84    42.5 3084.73    71.1 3073.69    86.4 3068.96    95.7    3067
     108 3067.99   130.2 3066.73     153 3062.11   169.4 3060.85   177.6 3058.73
   185.7 3057.95     198 3057.43   200.8 3057.89   214.4 3059.15   234.5 3058.21
   251.2 3058.91   267.6  3061.6   279.7 3061.34   287.7  3063.1   315.7 3063.94
   339.7 3060.36   351.7 3061.17   359.7 3062.88   363.7 3064.41   367.7 3067.19
   383.7 3079.18   395.7 3089.46   403.5 3094.74   419.7 3102.54     449  3119.5
#Mann= 4 ,-1,0
       0      .1       0   185.7    .045       0   200.8     .06       0
     230      .1       0
Bank Sta=185.7,200.8
XS Rating Curve= 0 ,0
Exp/Cntr(USF)=0,0
Exp/Cntr=0.3,0.1

Type RM Length L Ch R = 1 ,2953    ,236.2,242.8,248.1
XS GIS Cut Line= 4
2323675.38798884516224.3684882612323920.80553261516287.755646327
2324009.35523746 516327.85362588 2324094.7811468516380.732235032
#Sta/Elev= 30
       0 3082.37      21  3073.7    30.9 3070.41    42.1 3065.73    57.1 3061.52
    58.7  3061.3    66.9 3062.31      71 3062.27   112.9 3059.57   135.9 3060.06
   178.5 3058.33   199.1 3055.74   208.2 3053.48   221.3 3051.33   231.1 3050.36
     241 3051.58   248.7 3054.12   252.8 3054.82   261.6  3052.5     266 3052.35
   274.7  3055.6   299.4 3058.32   305.5 3060.06   309.9 3062.28   345.6 3083.75
   367.6 3094.98   398.8  3108.7   419.9 3117.39   438.7 3124.55   451.1 3128.54
#Mann= 5 ,-1,0
       0      .1       0     100     .06       0     200      .1       0
   221.3    .045       0     241      .1       0
#XS Ineff= 2 , 0
                           253.1          3059.1
Permanent Ineff=
       F       F
Bank Sta=221.3,241
XS Rating Curve= 0 ,0
Exp/Cntr(USF)=0,0
Exp/Cntr=0.3,0.1

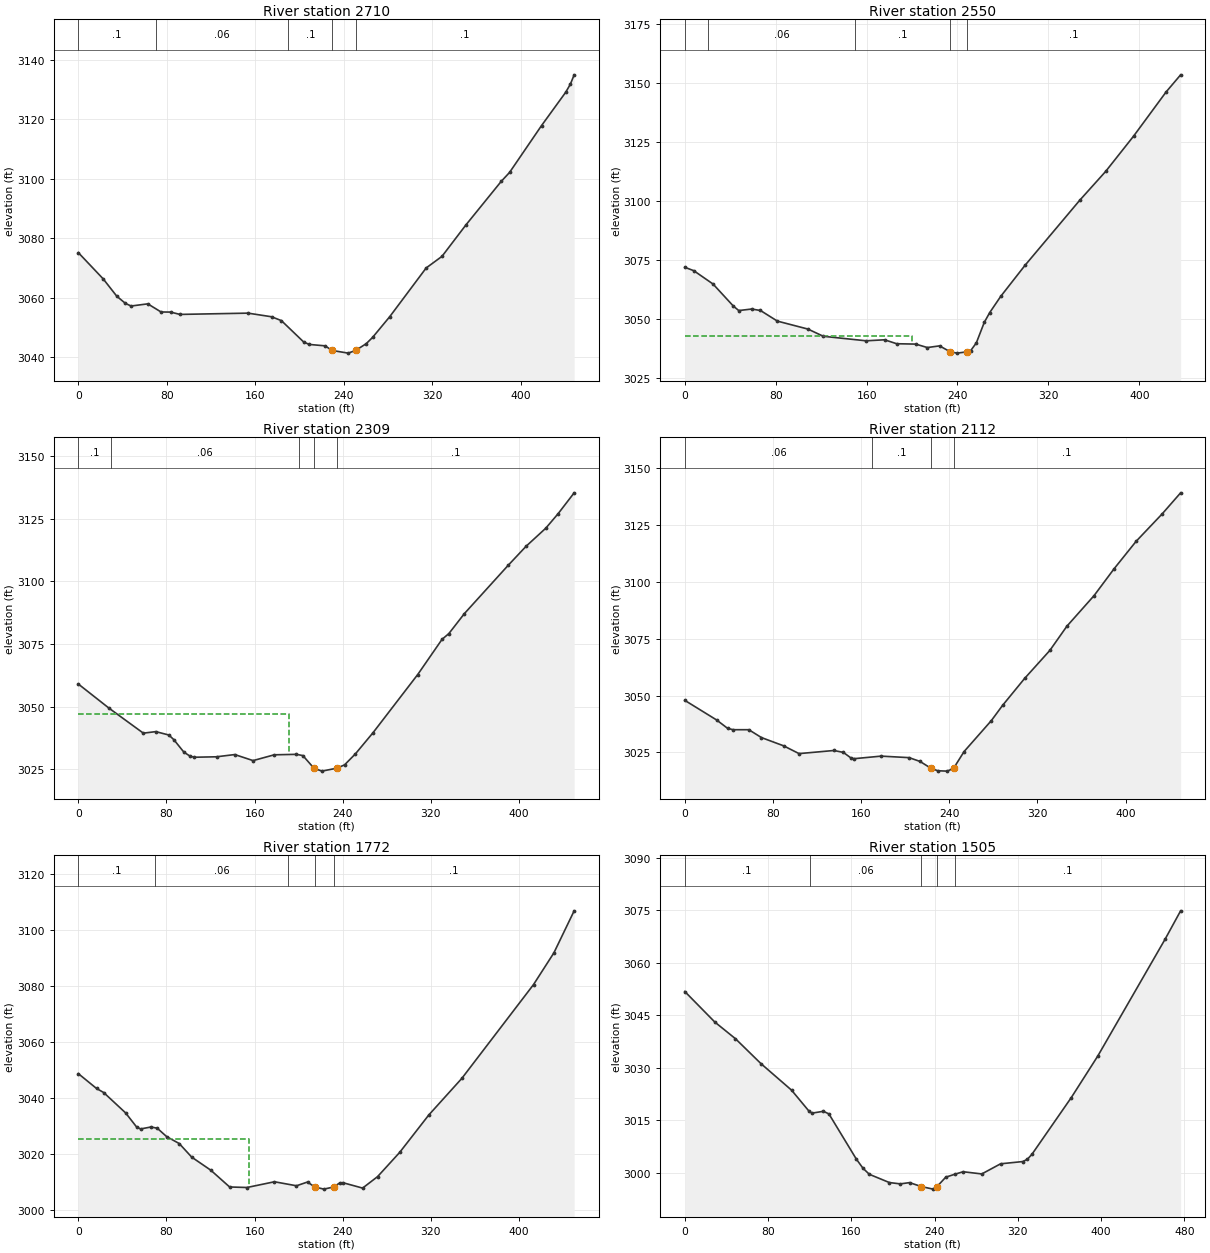
Type RM Length L Ch R = 1 ,2710    ,157.2,159.9,162.4
XS GIS Cut Line= 3
2323618.31524446516354.1931881772323879.50442177516553.933252305
2323913.54222057516668.428490736
#Sta/Elev= 30
       0 3075.12    22.5 3066.27    34.8 3060.43    42.6 3058.02    47.7 3057.14
    62.8 3057.87    74.8 3055.13    83.4  3055.1    91.9 3054.31   153.4 3054.74
   174.7 3053.52   183.6 3052.22   203.8    3045   208.8  3044.2   223.2 3043.72
   229.4 3042.17     244 3041.27   250.8 3042.19   260.3 3044.46     266 3046.55
   281.5 3053.52   314.5 3069.96   328.8 3073.87   350.4 3084.44   382.3  3099.1
   389.9 3102.14   418.8 3117.92   440.7 3129.17   444.9 3131.89   448.3 3135.02
#Mann= 5 ,-1,0
       0      .1       0      70     .06       0     190      .1       0
   229.4    .045       0   250.8      .1       0
Bank Sta=229.4,250.8
XS Rating Curve= 0 ,0
Exp/Cntr(USF)=0,0
Exp/Cntr=0.3,0.1

Type RM Length L Ch R = 1 ,2550    ,242.1,241,240.7
XS GIS Cut Line= 2
2323539.54406776516438.7083283352323831.96269906516762.699151183
#Sta/Elev= 30
       0 3071.87     7.9 3070.43    24.9 3064.75    42.7 3055.42    47.5  3053.5
    58.8 3054.15    66.6 3053.53    81.5 3049.02   108.4 3045.64   121.9 3042.58
   159.6 3040.66   175.8 3041.09   186.5 3039.42   203.3 3039.26   213.5  3037.8
   224.2 3038.51   233.8 3035.95   239.7 3035.43   248.6 3035.99   251.7 3036.54
   256.6 3039.78   263.6 3048.51   268.4 3052.66   278.1 3059.55   299.4 3072.68
   347.7 3100.38   370.4 3112.56     395 3127.55   423.6  3146.3   436.4 3153.58
#Mann= 5 ,-1,0
       0      .1       0      20     .06       0     150      .1       0
   233.8    .045       0   248.6      .1       0
#XS Ineff= 2 , 0
          199.65 3042.64
Permanent Ineff=
       F       F
Bank Sta=233.8,248.6
XS Rating Curve= 0 ,0
Exp/Cntr(USF)=0,0
Exp/Cntr=0.3,0.1

Type RM Length L Ch R = 1 ,2309    ,195.2,197,198.9
XS GIS Cut Line= 2
2323355.37763866516602.5239182312323666.29479179516927.839955175
#Sta/Elev= 30
       0 3059.04    27.9 3049.39      59 3039.44    70.3 3040.05    82.2 3038.69
    86.7 3036.83    95.8 3031.86   101.5 3030.24   105.4 3029.83   125.4 3030.01
     142  3030.9   158.6 3028.49   177.8  3030.8     198 3030.99   203.8 3030.49
   213.9 3025.42   221.1 3024.29   234.53025.455   241.6 3026.78   251.4 3031.14
   267.5 3039.64     308 3062.81   330.1 3076.87   336.3 3079.17   350.4 3087.15
     390 3106.34   406.4 3114.01   424.2 3121.19   435.4 3126.97     450 3135.32
#Mann= 5 ,-1,0
       0      .1       0      30     .06       0     200      .1       0
   213.9    .045       0   234.5      .1       0
#XS Ineff= 2 , 0
          191.55 3047.25
Permanent Ineff=
       F       F
Bank Sta=213.9,234.5
XS Rating Curve= 0 ,0
Exp/Cntr(USF)=0,0
Exp/Cntr=0.3,0.1

Type RM Length L Ch R = 1 ,2112    ,340.4,340.2,340.6
XS GIS Cut Line= 2
2323229.92309899516714.088189361 2323499.2073319517074.623904524
#Sta/Elev= 30
       0 3047.89    28.8  3039.3    38.8 3035.62    43.8    3035    58.1    3035
    69.6 3031.54    89.6 3027.94   103.7  3024.5   135.3 3025.87   143.9 3025.04
   150.8 3022.59   153.6 3022.27   178.2  3023.4   203.6 3022.73   213.5 3021.06
   223.5 3018.04   229.6 3016.97   238.2 3016.81   243.9 3018.02   253.5 3025.42
   278.2 3038.99   288.4 3045.68   308.4 3057.51   331.3 3069.81   346.8 3080.47
   371.4 3093.86   389.6 3105.67   409.6 3117.73   433.2 3129.75     450 3139.03
#Mann= 4 ,-1,0
       0     .06       0     170      .1       0   223.5    .045       0
   243.9      .1       0
Bank Sta=223.5,243.9
XS Rating Curve= 0 ,0
Exp/Cntr(USF)=0,0
Exp/Cntr=0.3,0.1

Type RM Length L Ch R = 1 ,1772    ,266.3,266.3,264.9
XS GIS Cut Line= 2
2322942.25112382516890.8698106952323212.45984852517250.713172583
#Sta/Elev= 30
       0 3048.79    16.5  3043.5      23 3042.04    42.9 3034.77    52.9 3029.72
    56.5 3029.03    65.9 3029.73    71.6  3029.3    80.2 3026.28    91.6 3023.81
   102.9 3018.96   120.2  3014.3   137.3  3008.3     153 3008.11     178 3010.16
     198 3008.73     208 3010.07   214.4 3008.33   222.8 3007.53   231.6 3008.28
   237.3 3009.76   240.1 3009.83     258  3007.9   271.6    3012   291.6 3020.63
     318 3033.99     348 3047.07   413.1  3080.6   431.6 3091.94     450 3106.96
#Mann= 5 ,-1,0
       0      .1       0      70     .06       0     190      .1       0
   214.4    .045       0   231.6      .1       0
#XS Ineff= 2 , 0
          154.49 3025.48
Permanent Ineff=
       F       F
Bank Sta=214.4,231.6
XS Rating Curve= 0 ,0
Exp/Cntr(USF)=0,0
Exp/Cntr=0.3,0.1

Type RM Length L Ch R = 1 ,1505    ,156.6,153.2,149
XS GIS Cut Line= 3
2322712.35469825517044.3141171452322884.06231717517243.421888022
2323077.69005765517333.537943343
#Sta/Elev= 30
       0 3051.75    28.8 3043.03    48.7 3038.25    73.2 3031.13   102.6 3023.55
   119.6 3017.46   122.4 3016.99   133.2 3017.51   138.5 3016.76   164.9 3003.82
   171.2 3001.25   177.3  2999.5   196.6 2997.14   207.1 2996.76     216 2997.12
   227.4 2995.99   238.6 2995.26  242.362995.981   250.8 2998.68     260 2999.56
   267.5 3000.23   285.4  2999.6   303.5  3002.5   324.8 3003.14   329.2 3003.79
   333.6 3005.21   371.4 3021.42   396.8 3033.26   461.6 3066.71   476.5 3074.81
#Mann= 5 ,-1,0
       0      .1       0     120     .06       0   227.4    .045       0
  242.36     .06       0     260      .1       0
Bank Sta=227.4,242.36
XS Rating Curve= 0 ,0
Exp/Cntr(USF)=0,0
Exp/Cntr=0.3,0.1

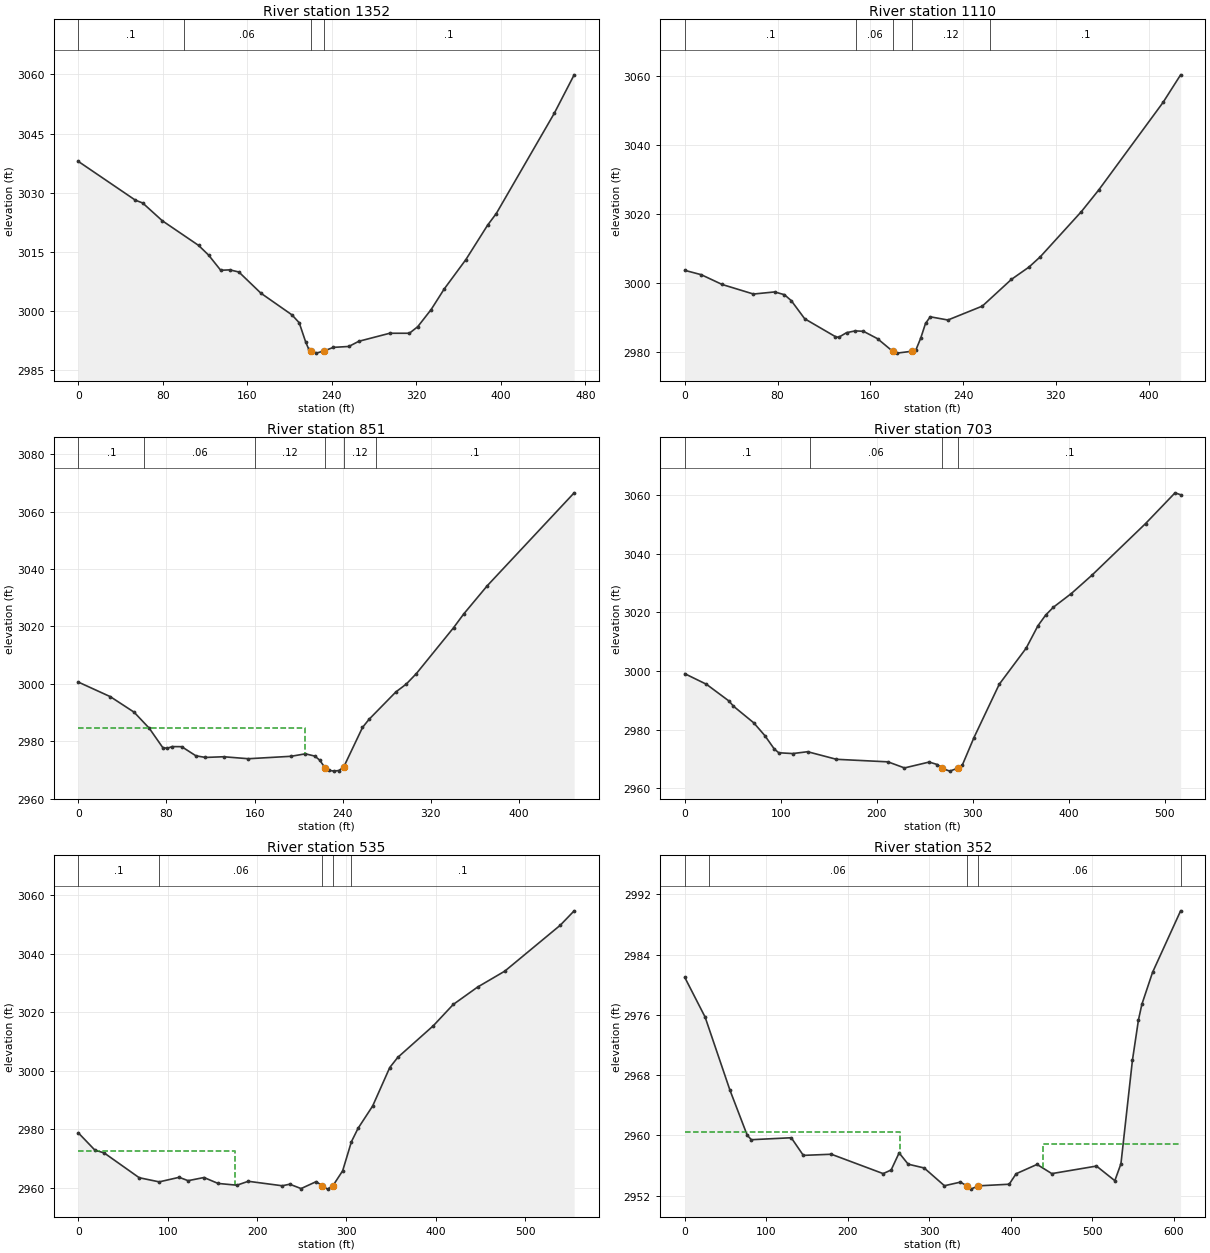
Type RM Length L Ch R = 1 ,1352    ,245.7,242,237.5
XS GIS Cut Line= 4
2322628.82176986517160.4743050892322746.25516903517325.037468697
 2322817.9616298517369.2911571912322995.72246601517412.462637287
#Sta/Elev= 30
       0 3037.93      54  3028.1    60.9 3027.39    79.5 3022.88   113.9 3016.62
   123.4 3014.15   134.8 3010.32   143.4 3010.43     152 3009.88   172.9  3004.5
   202.2 2999.02   209.1 2997.02   215.3 2992.08   218.2 2990.28   219.9 2989.94
   225.3 2989.31   232.6 2989.87   241.5 2990.77   256.1    2991   265.5 2992.31
   294.8 2994.35   313.4 2994.35   321.3 2996.01     334 3000.36   346.3 3005.55
   366.9 3013.04   387.5 3021.78   395.7 3024.72   450.5  3050.1   469.4 3059.89
#Mann= 4 ,-1,0
       0      .1       0     100     .06       0   219.9    .045       0
   232.6      .1       0
Bank Sta=219.9,232.6
XS Rating Curve= 0 ,0
Exp/Cntr(USF)=0,0
Exp/Cntr=0.3,0.1

Type RM Length L Ch R = 1 ,1110    ,257.8,259.6,261.8
XS GIS Cut Line= 5
2322496.18499149517411.6795521172322561.27370806517470.367550065
2322595.22720164517526.3259733742322653.86127167517540.608631458
2322824.30054347 517670.26286296
#Sta/Elev= 30
       0  3003.6    14.2 3002.33    32.2 2999.49    59.2 2996.71    77.5 2997.32
    85.9 2996.52    91.8  2994.8   103.4 2989.52   129.7 2984.36   132.6 2984.11
   139.5 2985.48   147.1    2986   154.1 2985.87   166.2 2983.73   179.4 2980.03
   182.9 2979.53     196 2980.08   199.4 2980.54   203.5 2983.92   207.6 2988.17
   211.7 2990.09   226.9 2989.16   256.6  2993.2   281.7 3000.98   296.8 3004.54
   306.6 3007.55     342 3020.67   357.1 3027.02   412.4  3052.4   427.6 3060.44
#Mann= 5 ,-1,0
       0      .1       0  147.64     .06       0   179.4    .045       0
     196     .12       0  263.44      .1       0
Bank Sta=179.4,196
XS Rating Curve= 0 ,0
Exp/Cntr(USF)=0,0
Exp/Cntr=0.3,0.1

Type RM Length L Ch R = 1 ,851     ,148.1,148,147.7
XS GIS Cut Line= 2
2322341.34027147517696.1115148992322758.00916844517866.073364421
#Sta/Elev= 30
       0  3000.6      29 2995.53    50.6 2990.12    64.4 2984.51    76.6 2977.79
    80.8 2977.53    85.1 2978.13    93.8  2978.1   106.7 2974.92   115.4 2974.35
   131.9 2974.59   154.3  2973.9   193.1 2974.75   206.1 2975.61   214.7 2974.81
   219.1 2973.39   223.9 2970.74   227.7 2969.84     232 2969.58   236.3 2969.79
   240.7 2970.89   257.9 2984.79   263.8 2987.61   288.2 2997.17   297.6  2999.9
   306.8 3003.57   340.5 3019.52   349.7  3024.3   371.2  3034.2     450 3066.54
#Mann= 6 ,-1,0
       0      .1       0      60     .06       0     160     .12       0
   223.9    .045       0   240.7     .12       0     270      .1       0
#XS Ineff= 2 , 0
          205.92 2984.76
Permanent Ineff=
       F       F
Bank Sta=223.9,240.7
XS Rating Curve= 0 ,0
Exp/Cntr(USF)=0,0
Exp/Cntr=0.3,0.1

Type RM Length L Ch R = 1 ,703     ,168.1,168,166.9
XS GIS Cut Line= 5
 2322324.1264777517722.2659850812322432.14441081517894.099565001
2322552.41942625517941.0431217962322730.89671964517944.816987359
2322728.71578749517939.400185136
#Sta/Elev= 30
       0 2999.06    22.5 2995.46      46 2989.74    50.7 2987.96    71.8 2982.29
    83.4 2977.91    93.2 2973.34    97.9 2972.06   112.4 2971.79   127.9 2972.42
   157.9 2969.83   211.6 2968.96   228.8 2966.88   254.5 2968.89   263.1 2968.03
     268 2966.72     276 2965.79   284.6 2966.84   288.9 2967.74   301.1  2977.2
   327.5 2995.46   355.5 3007.77   367.8 3015.44   375.8 3019.06   383.8 3021.74
   402.5 3026.42   423.9 3032.66   479.9 3050.34   510.6 3060.83   516.4 3060.17
#Mann= 4 ,-1,0
       0      .1       0     130     .06       0     268    .045       0
   284.6      .1       0
Bank Sta=268,284.6
XS Rating Curve= 0 ,0
Exp/Cntr(USF)=0,0
Exp/Cntr=0.3,0.1

Type RM Length L Ch R = 1 ,535     ,182.3,182.8,182.9
XS GIS Cut Line= 4
2322221.31822948517951.4999839512322341.61216814518040.049688797
2322489.47346774518090.1721632392322714.18922815 517982.40884319
#Sta/Elev= 30
       0 2978.81    18.4 2972.95      29 2971.92    68.1 2963.47    90.5 2962.05
   112.8 2963.61   122.8 2962.46   140.6 2963.54   156.3 2961.52   177.4 2960.91
   190.1 2962.25   228.1 2960.72   236.5 2961.25   249.2 2959.76   266.1 2962.13
   273.1 2960.66   278.8 2959.57   284.8 2960.73   295.7 2965.83   305.5 2975.77
   312.9 2980.34   329.3 2988.01   348.4 3001.14   357.3 3004.59   397.2 3015.45
   419.4  3022.7   446.6 3028.64   477.1  3034.1   539.1 3049.78   554.7 3054.72
#Mann= 5 ,-1,0
       0      .1       0    90.5     .06       0   273.1    .045       0
   284.8     .06       0   305.5      .1       0
#XS Ineff= 2 , 0
             175 2972.75
Permanent Ineff=
       F       F
Bank Sta=273.1,284.8
XS Rating Curve= 0 ,0
Exp/Cntr(USF)=0,0
Exp/Cntr=0.3,0.1

Type RM Length L Ch R = 1 ,352     ,297.2,297.2,297.2
XS GIS Cut Line= 4
2322188.17415851518006.5362040972322343.54005223518226.203282691
2322497.74412777518283.9979653612322660.43895509 518220.98236323
#Sta/Elev= 30
       0 2980.96    24.9  2975.7    55.4 2965.99    76.5 2960.03    81.6 2959.42
   130.6 2959.68   145.4 2957.34   179.8 2957.49   243.3 2954.92   253.1  2955.4
   262.9 2957.67     274 2956.17   293.6 2955.67   318.5 2953.31   338.1 2953.79
345.6291 2953.32   350.9 2952.86360.02642953.294   397.9 2953.51   406.4  2954.9
   432.1 2956.14   450.2 2954.92     505 2955.92   527.5 2953.98     535 2956.23
   549.1 2969.97   556.5 2975.33   560.7  2977.4   573.8 2981.64   608.2  2989.8
#Mann= 5 ,-1,0
       0      .1       0      30     .06       0345.6291    .045       0
360.0264     .06       0  608.21      .1       0
#XS Ineff= 2 , 0
          264.23 2960.39  439.72         2958.91
Permanent Ineff=
       F       F
Bank Sta=345.6291,360.0264
XS Rating Curve= 0 ,0
Exp/Cntr(USF)=0,0
Exp/Cntr=0.3,0.1

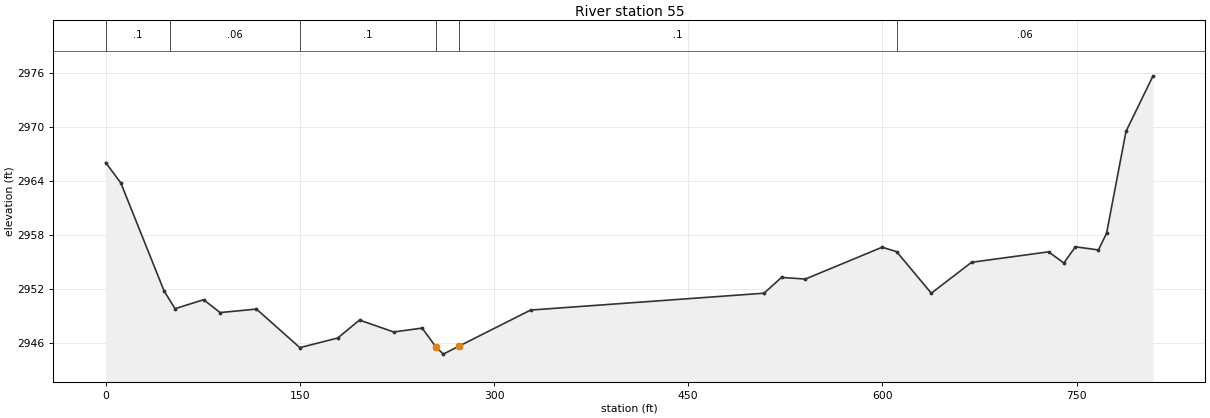
Type RM Length L Ch R = 1 ,55      ,,,
XS GIS Cut Line= 4
2322072.51399589518182.0215445572322140.27380295518398.571787418
2322294.94846273518454.7129602252322670.08906425518271.047313443
#Sta/Elev= 30
       0 2966.06    11.7  2963.8    45.2 2951.79    53.6 2949.84    75.7 2950.84
    88.4 2949.41   116.5  2949.8     150 2945.52   179.3 2946.59   196.1 2948.58
   222.5 2947.26   244.5 2947.69   254.92945.637   260.8  2944.8   272.6 2945.66
   328.3 2949.69   508.6 2951.56   522.1 2953.31   540.5 2953.13   599.8 2956.66
     611 2956.17   637.8 2951.56   668.9 2954.99   728.4 2956.15   740.2 2954.91
   749.1 2956.71   766.9 2956.36   773.2 2958.21   788.2 2969.51   809.1 2975.68
#Mann= 6 ,-1,0
       0      .1       0      50     .06       0     150      .1       0
   254.9    .045       0   272.6      .1       0  611.45     .06       0
Bank Sta=254.9,272.6
XS Rating Curve= 0 ,0
Exp/Cntr(USF)=0,0
Exp/Cntr=0.3,0.1
LCMann Table=0

Chan Stop Cuts=-1
Use User Specified Reach Order=0
Composite Channel Slope=5